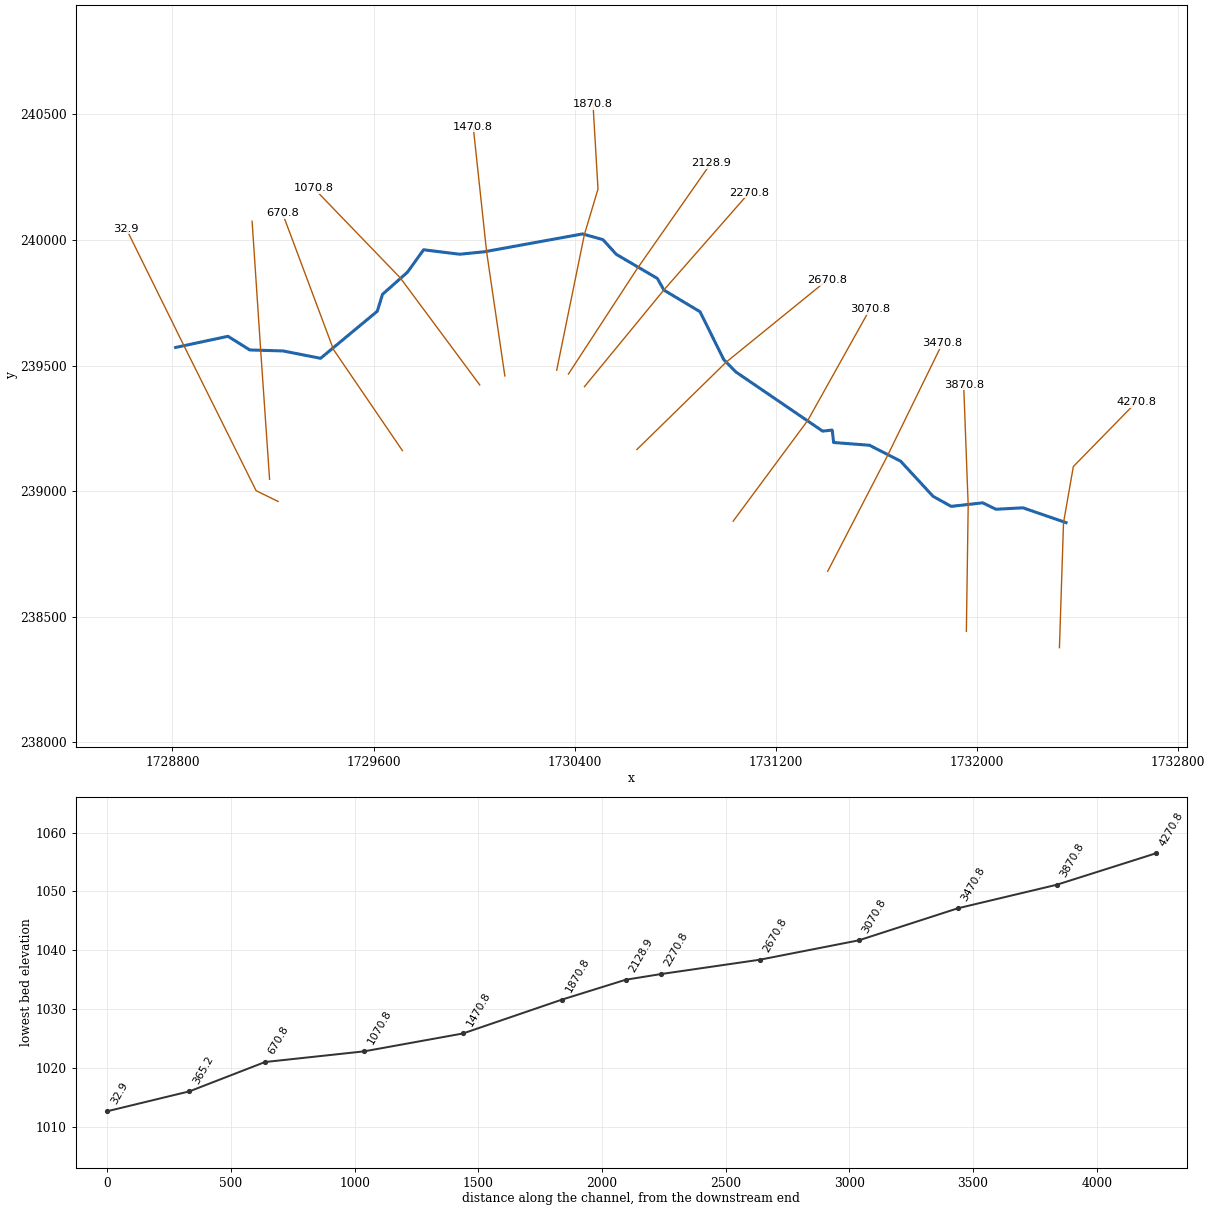
--- LostCrTr1.prj (project) ---

Proj Title=LostCrTr1
Current Plan=p01
Geom File=g01
Flow File=f01
Plan File=p01
DSS Export Rating Curves=0
DSS Export Rating Curve Sorted=0
DSS Export Volume Flow Curves=0
DXF OffsetX=0
DXF OffsetY=0
DXF ScaleX=0
DXF ScaleY=0

--- LostCrTr1.p01 (plan) ---

Plan Title=Floodplain
Program Version=4.00
Geom File=g01
Flow File=f01
K Sum by GR=0
Std Step Tol=0.01
Critical Tol=0.01
Num of Std Step Trials=20
Max Error Tol=0.3
Flow Tol Ratio=0.001
Split Flow NTrial=30
Split Flow Tol=0.02
Split Flow Ratio=0.02
Log Output Level=0
Friction Slope Method=1
Unsteady Friction Slope Method=2
Unsteady Bridges Friction Slope Method=1
Global Log Level=0
CheckData=False
Run HTab=0
Run UNet=0
Run PostProcess=0
UNET Theta=0
UNET Theta Warmup=0
UNET ZTol=0
UNET ZSATol=0
UNET MxIter=0
UNET MaxInSteps=0
UNET DtIC=0
UNET DtMin=0
UNET MaxCRTS=0
UNET WFStab=0
UNET SFStab=0
UNET WFX=0
UNET SFX=0
UNET DSS MLevel=0
UNET DZMax Abort=0
UNET Convert EG Bridges=0
UNET Use Existing IB Tables=0
UNET Froude Limit=0
UNET Froude Power=0
Write IC File=0
Echo Input=False
Echo Output=False
Write Detailed=0

--- LostCrTr1.f01 (steady flow) ---

Flow Title=NFF Regression Equation
Program Version=4.00
Number of Profiles=1
Profile Names=P100yr
River Rch & RM=LostCrTr1,Main      ,4270.8
641.7156
River Rch & RM=LostCrTr1,Main      ,3870.8
847.6105
River Rch & RM=LostCrTr1,Main      ,2128.9
907.6610
River Rch & RM=LostCrTr1,Main      ,1870.8
1199.365
River Rch & RM=LostCrTr1,Main      ,365.2
1232.403
River Rch & RM=LostCrTr1,Main      ,32.9
2283.895
Boundary for River Rch & Prof#=LostCrTr1,Main      ,1
Up Type=0
Dn Type=3
Dn Slope=0.011152

--- LostCrTr1.g01 (geometry) ---

Geom Title=USGS 3m DEM
Program Version=4.00

River Reach=LostCrTr1     ,Main
Reach XY= 30
     1732354.114      238874.671     1732182.863      238933.657
     1732075.355      238927.949     1732022.634      238953.509
     1731897.341      238939.402     1731825.395      238979.261
     1731695.944      239119.594     1731572.433      239182.766
     1731429.857      239193.724     1731424.052      239243.237
     1731386.058      239239.059     1731040.960      239474.716
     1730992.660      239524.021     1730898.587      239714.424
     1730754.999      239800.417     1730728.708      239847.101
     1730565.458      239943.060     1730512.294      240001.655
     1730431.294      240024.318     1730039.288      239953.092
     1729942.347      239943.521     1729799.032      239961.214
     1729734.647      239871.728     1729635.542      239783.733
     1729614.836      239716.488     1729389.278      239529.055
     1729239.944      239558.356     1729107.845      239562.290
     1729020.804      239616.656     1728812.812      239572.163

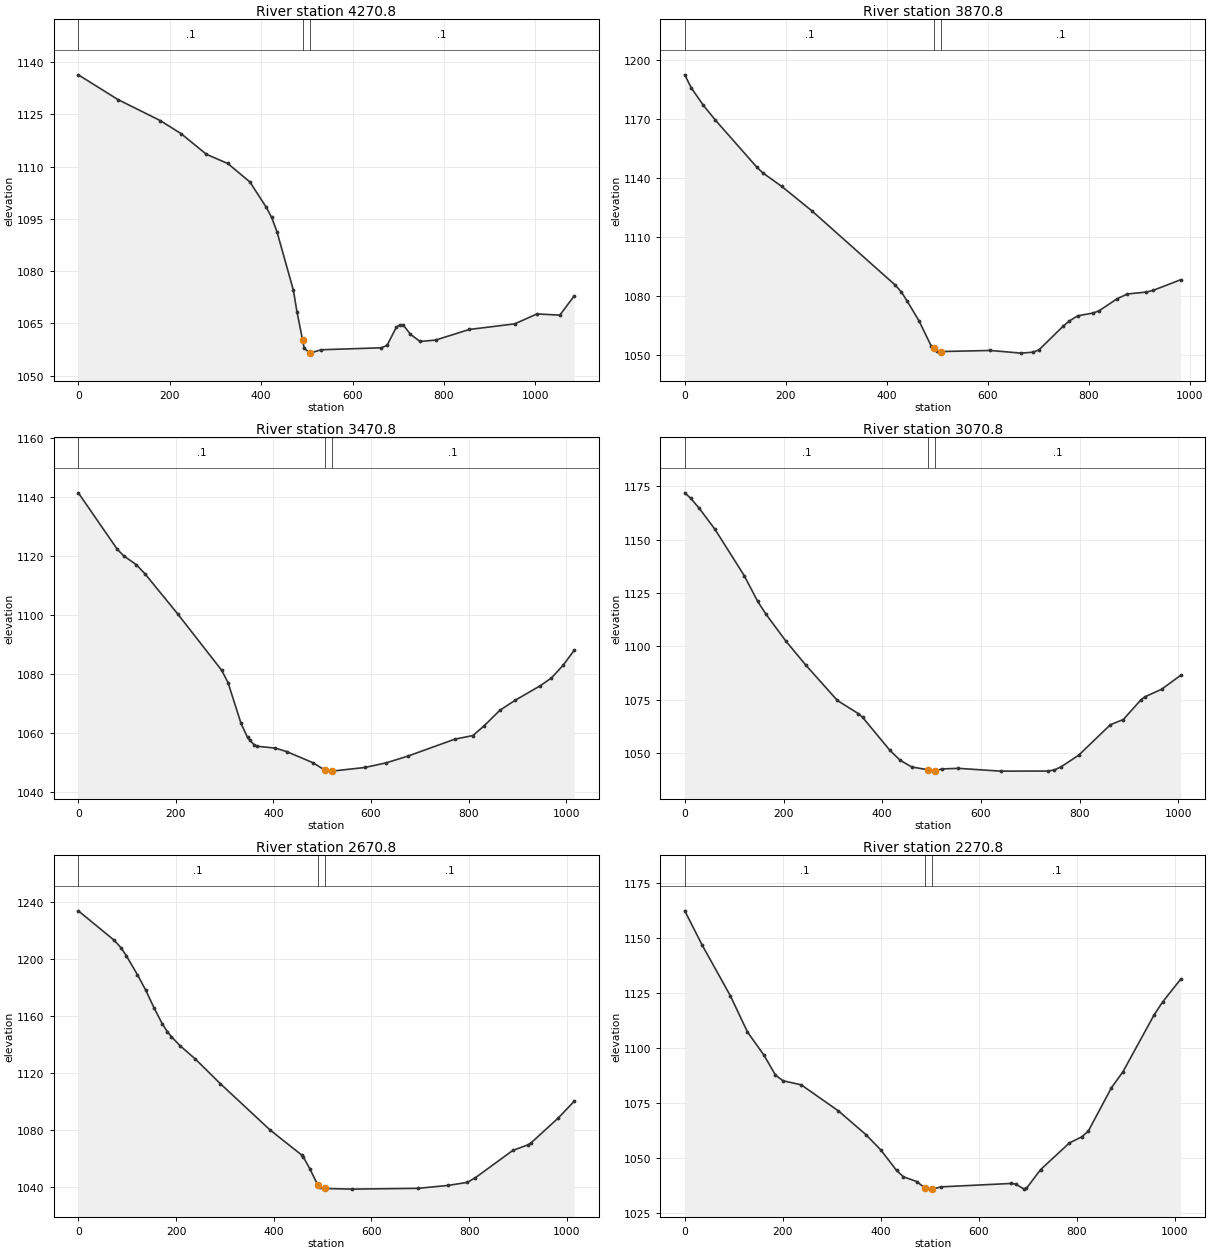
Type RM Length L Ch R = 1 ,4270.8,399.909,400,404.54
XS GIS Cut Line= 4
     1732327.810      238376.660     1732344.114      238874.671
     1732383.124      239097.990     1732634.464      239355.321
#Sta/Elev= 30
       0 1136.37    87.2 1129.23   179.5 1123.22   225.2 1119.44   280.3 1113.54
   326.9 1110.91   375.3 1105.62   411.0 1098.37   422.9 1095.43   434.7 1091.26
   470.4 1074.56   478.3 1068.31   490.8 1060.11   494.1 1057.91   505.8 1056.51
   506.1 1056.46   531.7 1057.43   662.8 1057.99   675.4 1058.70   695.9 1063.96
   703.3 1064.51   711.0 1064.49   726.4 1061.90   747.4 1059.81   781.4 1060.20
   855.1 1063.25   954.7 1064.86  1003.4 1067.72  1053.3 1067.37  1084.7 1072.87
#Mann= 3 , 0 , 0
       0     0.1       0   490.8   0.045       0   505.8     0.1       0
Bank Sta=   490.8,   505.8
Exp/Cntr=0.3,0.1

Type RM Length L Ch R = 1 ,3870.8,410.099,400,389.158
XS GIS Cut Line= 3
     1731957.686      238442.164     1731964.939      238942.884
     1731946.962      239423.631
#Sta/Elev= 30
       0 1192.59    12.8 1185.97    36.6 1177.16    60.3 1169.66   143.2 1145.49
   155.3 1142.59   191.9 1135.90   252.1 1123.36   416.5 1085.77   428.4 1082.38
   440.3 1077.61   464.0 1067.46   487.8 1054.85   493.3 1053.78   499.6 1052.09
   508.3 1051.94   605.1 1052.48   666.0 1051.13   689.7 1051.61   701.6 1052.85
   749.1 1064.79   761.0 1067.36   777.9 1070.09   808.6 1071.51   820.4 1072.65
   856.1 1078.76   876.6 1081.21   913.6 1082.14   927.4 1083.03   981.9 1088.42
#Mann= 3 , 0 , 0
       0     0.1       0   493.3   0.045       0   508.3     0.1       0
Bank Sta=   493.3,   508.3
Exp/Cntr=0.3,0.1

Type RM Length L Ch R = 1 ,3470.8,387.234,400,384.117
XS GIS Cut Line= 3
     1731406.260      238681.062     1731641.643      239136.546
     1731862.662      239589.057
#Sta/Elev= 30
       0 1141.47    79.6 1122.39    92.8 1120.12   119.0 1117.10   137.1 1113.93
   203.5 1100.46   293.5 1081.39   306.8 1077.17   333.5 1063.29   346.9 1058.55
   351.7 1057.55   360.3 1056.09   366.2 1055.56   403.5 1054.94   427.1 1053.76
   481.0 1049.97   505.2 1047.49   520.2 1047.13   587.8 1048.38   631.4 1049.96
   675.8 1052.24   771.6 1057.96   808.9 1059.20   831.3 1062.41   864.1 1067.77
   895.4 1071.15   947.1 1076.10   969.8 1078.73   993.6 1083.01  1016.3 1088.08
#Mann= 3 , 0 , 0
       0     0.1       0   505.2   0.045       0   520.2     0.1       0
Bank Sta=   505.2,   520.2
Exp/Cntr=0.3,0.1

Type RM Length L Ch R = 1 ,3070.8,403.591,400,391.431
XS GIS Cut Line= 3
     1731030.342      238880.604     1731327.399      239282.424
     1731573.368      239723.497
#Sta/Elev= 30
       0 1171.87    12.0 1169.32    29.0 1164.72    61.3 1154.75   120.3 1133.18
   147.8 1121.06   164.6 1115.06   205.0 1102.48   244.9 1091.37   309.1 1074.76
   351.6 1068.59   360.1 1066.91   415.6 1051.42   436.5 1046.75   459.9 1043.63
   492.2 1042.36   507.2 1041.91   522.0 1042.73   554.4 1042.99   639.8 1041.69
   735.0 1041.73   748.6 1042.22   762.2 1043.66   798.2 1049.15   862.3 1063.39
   888.5 1065.83   923.4 1074.81   932.1 1076.44   966.1 1079.98  1004.7 1086.50
#Mann= 3 , 0 , 0
       0     0.1       0   492.2   0.045       0   507.2     0.1       0
Bank Sta=   492.2,   507.2
Exp/Cntr=0.3,0.1

Type RM Length L Ch R = 1 ,2670.8,397.397,400,403.931
XS GIS Cut Line= 3
     1730647.188      239165.713     1731002.595      239513.878
     1731403.970      239840.292
#Sta/Elev= 30
       0 1233.78    72.8 1213.30    87.2 1207.96    98.0 1202.36   121.1 1188.89
   138.1 1177.99   155.0 1165.67   172.0 1154.36   182.0 1149.03   190.4 1145.49
   208.3 1139.07   239.8 1129.65   290.7 1112.43   392.5 1079.93   457.6 1062.22
   460.4 1061.04   474.3 1052.42     490 1041.36   494.3 1039.55     505 1038.85
   560.1 1038.40   695.1 1038.96   757.4 1041.02   796.4 1043.16   812.8 1046.44
   889.2 1065.55   919.9 1069.45   926.8 1070.90   982.1 1088.25  1014.9 1100.06
#Mann= 3 , 0 , 0
       0     0.1       0     490   0.045       0     505     0.1       0
Bank Sta=     490,     505
Exp/Cntr=0.3,0.1

Type RM Length L Ch R = 1 ,2270.8,139.281,141.934,144.93
XS GIS Cut Line= 3
     1730438.756      239416.019     1730754.549      239800.952
     1731093.261      240187.694
#Sta/Elev= 30
       0 1162.36    35.0 1146.98    93.0 1123.79   127.8 1107.37   161.5 1096.84
   185.1 1087.75   200.5 1085.16   237.4 1083.35   313.4 1071.52   369.4 1060.77
   400.1 1053.74   432.2 1044.47   446.2 1041.56   473.6 1039.39   490.4 1036.42
   505.4 1036.02   523.7 1037.00   665.7 1038.53   675.6 1038.25   692.5 1035.96
   697.3 1036.31   726.1 1044.81   785.0 1056.94   810.3 1059.73   823.5 1062.29
   870.9 1082.05   894.4 1089.32   957.3 1114.87   975.3 1120.99  1012.0 1131.28
#Mann= 3 , 0 , 0
       0     0.1       0   490.4   0.045       0   505.4     0.1       0
Bank Sta=   490.4,   505.4
Exp/Cntr=0.3,0.1

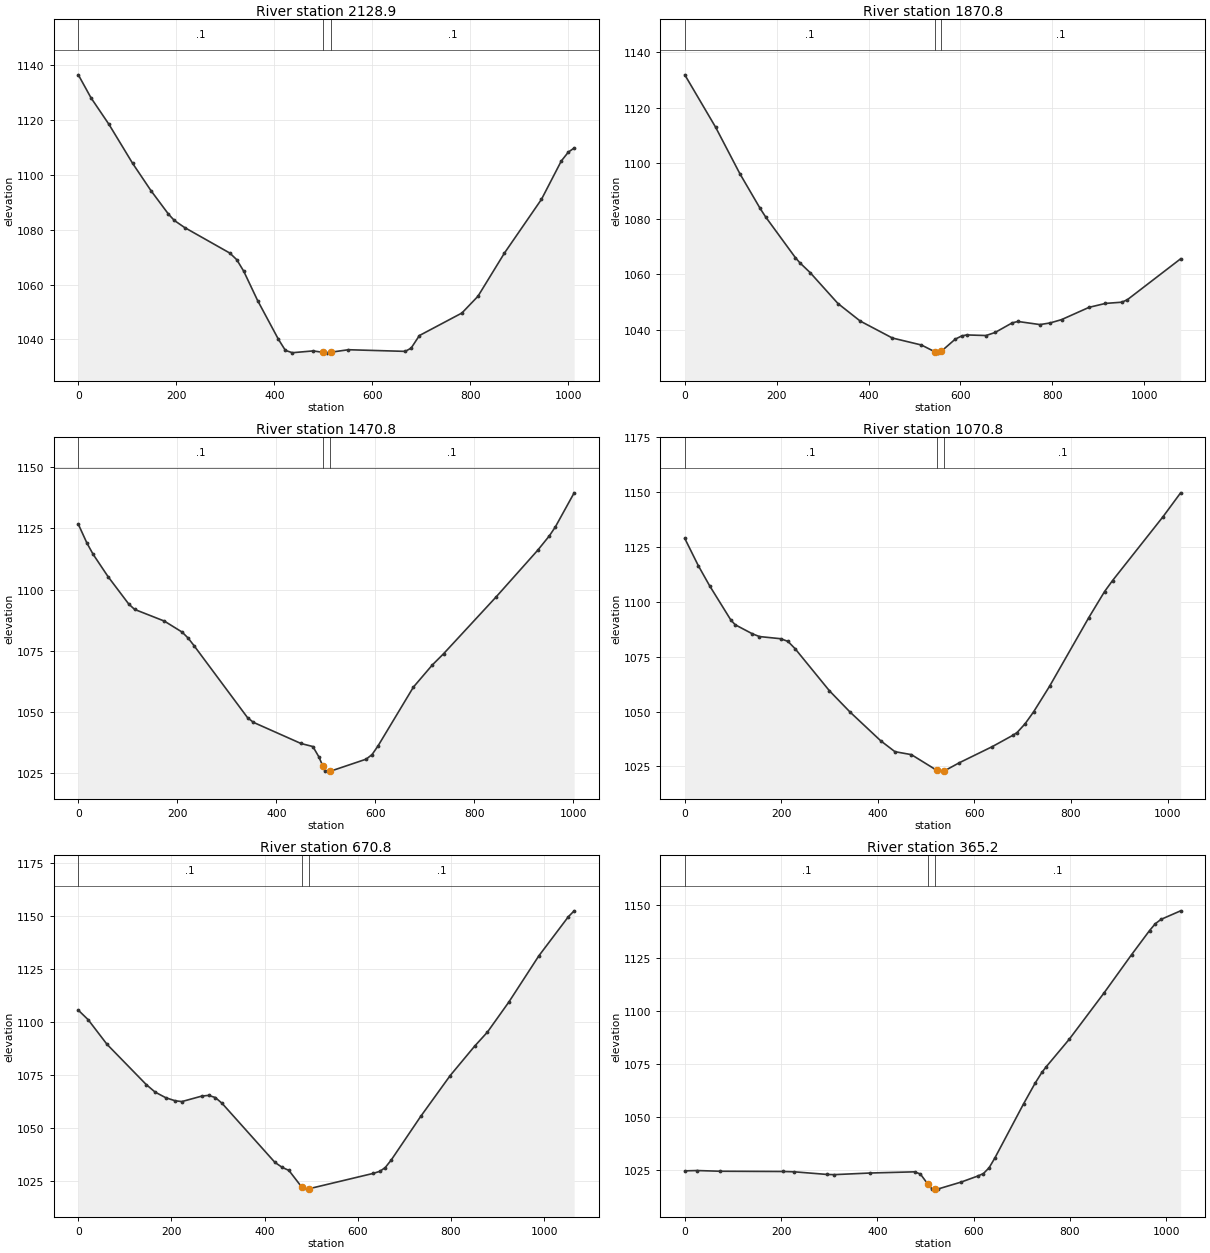
Type RM Length L Ch R = 1 ,2128.9,247.306,258.066,266.7
XS GIS Cut Line= 3
     1730375.015      239466.229     1730646.744      239883.436
     1730941.056      240304.952
#Sta/Elev= 30
       0 1136.50    25.9 1128.10    62.5 1118.44   110.9 1104.19   148.3 1094.25
   184.0 1085.69   195.9 1083.39   217.0 1080.80   309.2 1071.49   323.4 1069.07
   337.6 1064.87   365.9 1054.19   408.4 1040.04   422.6 1036.00   436.8 1035.15
   479.3 1035.81   500.2 1035.26   507.8 1035.00   515.2 1035.33   551.3 1036.24
   667.1 1035.64   679.2 1036.82   696.1 1041.41   782.9 1049.63   815.6 1055.73
   869.8 1071.52   945.3 1091.10   985.7 1105.06  1000.1 1108.31  1012.0 1109.81
#Mann= 3 , 0 , 0
       0     0.1       0   500.2   0.045       0   515.2     0.1       0
Bank Sta=   500.2,   515.2
Exp/Cntr=0.3,0.1

Type RM Length L Ch R = 1 ,1870.8,392.202,400,408.935
XS GIS Cut Line= 4
     1730328.401      239481.649     1730438.558      240021.924
     1730492.632      240202.854     1730472.800      240541.647
#Sta/Elev= 30
       0 1131.82    67.0 1112.99   119.9 1096.23   163.9 1083.76   176.0 1080.66
   240.7 1066.02   250.7 1064.12   273.0 1060.60   333.5 1049.48   382.0 1043.16
   452.0 1037.06   515.3 1034.54   543.9 1032.15   551.4 1031.62   558.9 1032.34
   588.8 1036.65   602.9 1037.80   613.6 1038.17   655.9 1037.96   675.6 1039.05
   712.7 1042.50   725.1 1043.02   773.3 1041.90   795.0 1042.47   820.3 1043.68
   880.3 1048.11   916.0 1049.52   951.7 1049.96   963.6 1050.85  1079.6 1065.58
#Mann= 3 , 0 , 0
       0     0.1       0   543.9   0.045       0   558.9     0.1       0
Bank Sta=   543.9,   558.9
Exp/Cntr=0.3,0.1

Type RM Length L Ch R = 1 ,1470.8,389.912,400,416.308
XS GIS Cut Line= 3
     1730122.254      239458.527     1730049.493      239954.183
     1729996.285      240451.764
#Sta/Elev= 30
       0 1126.74    17.2 1119.11    29.7 1114.51    59.9 1105.37   101.8 1094.14
   113.7 1091.94   173.7 1087.17   209.7 1082.66   221.7 1080.24   233.7 1077.13
   341.7 1047.73   353.7 1045.79   449.7 1037.16   473.7 1035.91   485.7 1031.74
   493.5 1028.07   497.7 1026.12   508.5 1025.89   509.6 1025.87   581.3 1030.76
   593.2 1032.63   605.2 1036.15   676.8 1060.22   715.1 1069.28   738.0 1073.90
   844.0 1097.09   927.6 1116.07   951.4 1122.02   963.4 1125.64  1001.4 1139.57
#Mann= 3 , 0 , 0
       0     0.1       0   493.5   0.045       0   508.5     0.1       0
Bank Sta=   493.5,   508.5
Exp/Cntr=0.3,0.1

Type RM Length L Ch R = 1 ,1070.8,401.002,400,390.584
XS GIS Cut Line= 3
     1730022.350      239423.030     1729706.736      239848.786
     1729361.906      240206.866
#Sta/Elev= 30
       0 1128.94    28.0 1116.52    51.2 1107.44    95.5 1091.70   104.4 1089.58
   139.9 1085.46   154.6 1084.20   199.0 1083.20   213.8 1081.97   228.5 1078.66
   299.6 1059.47   342.0 1049.84   405.9 1036.65   435.3 1031.70   469.4 1030.35
   522.5 1023.13   534.3 1022.83   537.5 1022.92   568.5 1026.63   637.0 1034.01
   679.9 1039.21   688.3 1040.42   704.8 1044.40   722.6 1049.88   755.5 1061.49
   836.6 1092.74   869.6 1104.74   886.1 1109.74   990.6 1138.84  1027.1 1149.74
#Mann= 3 , 0 , 0
       0     0.1       0   522.5   0.045       0   537.5     0.1       0
Bank Sta=   522.5,   537.5
Exp/Cntr=0.3,0.1

Type RM Length L Ch R = 1 ,670.8,317.754,305.644,299.015
XS GIS Cut Line= 3
     1729714.628      239161.698     1729440.638      239564.031
     1729238.267      240105.782
#Sta/Elev= 30
       0 1105.59    21.2 1101.07    61.5 1089.48   145.9 1070.42   164.8 1066.89
   188.1 1064.18   207.9 1062.78   222.3 1062.40   265.4 1065.01   279.7 1065.32
   294.1 1064.31   308.5 1061.60   422.1 1033.65   437.8 1031.29   452.1 1029.87
   479.3 1022.08   490.7 1021.02   494.3 1021.15   633.6 1028.48   647.6 1029.46
   659.0 1031.24   671.7 1034.76   735.0 1055.38   798.4 1074.71   850.6 1088.53
   878.3 1095.24   924.4 1109.48   988.5 1131.22  1051.9 1149.72  1064.5 1152.55
#Mann= 3 , 0 , 0
       0     0.1       0   479.3   0.045       0   494.3     0.1       0
Bank Sta=   479.3,   494.3
Exp/Cntr=0.3,0.1

Type RM Length L Ch R = 1 ,365.2,323.626,332.303,340.944
XS GIS Cut Line= 3
     1729186.503      239047.207     1729150.735      239566.648
     1729116.954      240075.007
#Sta/Elev= 30
       0 1024.65    25.2 1024.81    72.8 1024.48   203.7 1024.36   227.5 1024.21
   295.7 1022.96   310.8 1022.88   384.7 1023.64   477.4 1024.20   489.3 1023.16
   505.3 1018.25   513.1 1016.23   520.3 1016.10   525.0 1016.04   574.1 1019.38
   608.3 1022.20   620.2 1023.38   632.1 1026.14   644.0 1030.74   703.5 1056.23
   727.3 1065.91   741.5 1071.07   751.1 1073.88   798.7 1086.81   870.1 1108.40
   927.8 1126.61   965.3 1138.03   977.2 1141.24   989.1 1143.30  1029.8 1147.33
#Mann= 3 , 0 , 0
       0     0.1       0   505.3   0.045       0   520.3     0.1       0
Bank Sta=   505.3,   520.3
Exp/Cntr=0.3,0.1

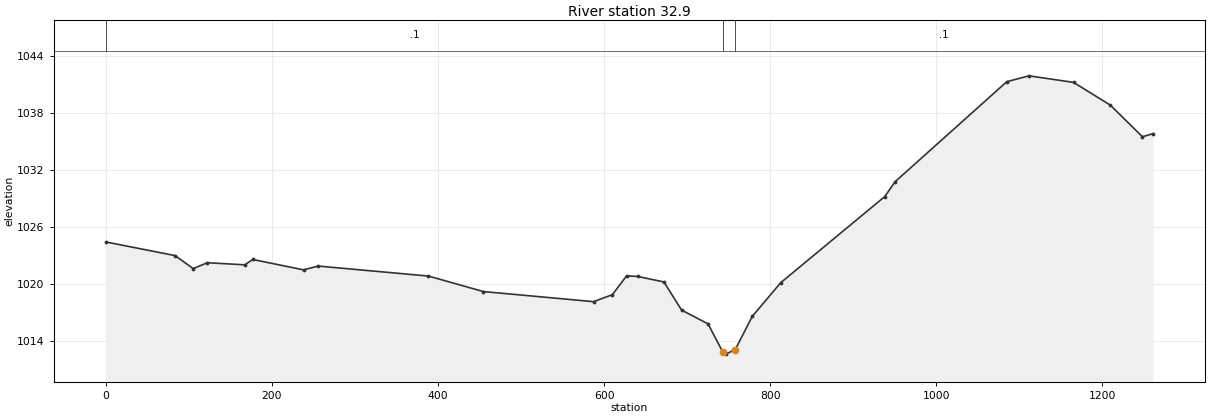
Type RM Length L Ch R = 1 ,32.9,33.078,32.86,32.713
XS GIS Cut Line= 4
     1729220.504      238958.913     1729132.913      239001.882
     1728841.898      239587.469     1728616.669      240044.462
#Sta/Elev= 30
       0 1024.44    83.3 1023.01   105.2 1021.64   122.1 1022.26   167.2 1022.04
   177.0 1022.60   238.0 1021.51   255.5 1021.91   388.4 1020.86   454.7 1019.23
   587.3 1018.17   610.0 1018.91   627.0 1020.88   640.3 1020.82   672.0 1020.24
   693.3 1017.28   725.1 1015.84   742.9 1012.87   746.4 1012.66   757.9 1013.14
   778.3 1016.62   812.5 1020.15   937.9 1029.21   950.5 1030.78  1084.8 1041.27
  1111.6 1041.89  1165.3 1041.20  1209.6 1038.81  1248.2 1035.49  1261.0 1035.82
#Mann= 3 , 0 , 0
       0     0.1       0   742.9   0.045       0   757.9     0.1       0
Bank Sta=   742.9,   757.9
Exp/Cntr=0.3,0.1